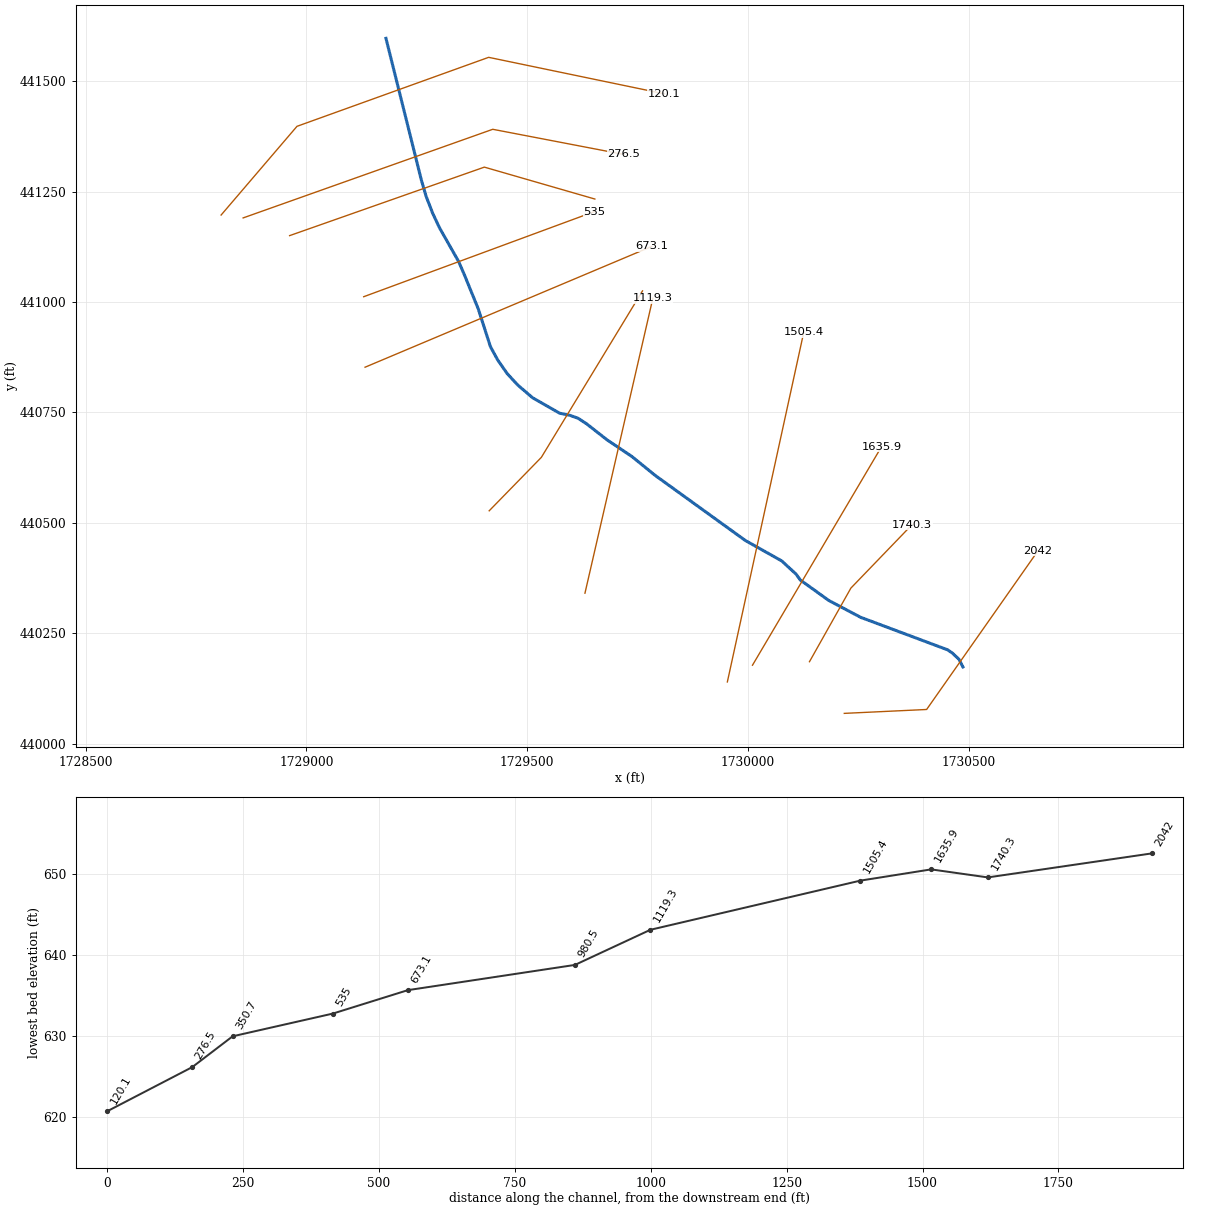
--- DICKSCK.prj (project) ---

Proj Title=DICKSCK
Current Plan=p01
Default Exp/Contr=0,0
English Units
Geom File=g01
Flow File=f01
Plan File=p01
BEGIN DESCRIPTION:
END DESCRIPTION:
DSS Export Rating Curves= 0
DSS Export Rating Curve Sorted= 0
DSS Export Volume Flow Curves= 0
DXF OffsetX= 0
DXF OffsetY= 0
DXF ScaleX= 0
DXF ScaleY= 0

--- DICKSCK.p01 (plan) ---

Plan Title=Floodplain
Program Version=4.00
Geom File=g01
Flow File=f01
K Sum by GR=0
Std Step Tol=0.01
Critical Tol=0.01
Num of Std Step Trials=20
Max Error Tol=0.3
Flow Tol Ratio=0.001
Split Flow NTrial=30
Split Flow Tol=0.02
Split Flow Ratio=0.02
Log Output Level=0
Friction Slope Method=1
Unsteady Friction Slope Method=2
Unsteady Bridges Friction Slope Method=1
Global Log Level=0
CheckData=False
Run HTab=0
Run UNet=0
Run PostProcess=0
UNET Theta=0
UNET Theta Warmup=0
UNET ZTol=0
UNET ZSATol=0
UNET MxIter=0
UNET MaxInSteps=0
UNET DtIC=0
UNET DtMin=0
UNET MaxCRTS=0
UNET WFStab=0
UNET SFStab=0
UNET WFX=0
UNET SFX=0
UNET DSS MLevel=0
UNET DZMax Abort=0
UNET Convert EG Bridges=0
UNET Use Existing IB Tables=0
UNET Froude Limit=0
UNET Froude Power=0
Write IC File=0
Echo Input=False
Echo Output=False
Write Detailed=0

--- DICKSCK.f01 (steady flow) ---

Flow Title=NFF Regression Equation
Program Version=4.10
Number of Profiles= 1
Profile Names=P100yr
River Rch & RM=DICKSCK,Main            ,2042
818.2642
River Rch & RM=DICKSCK,Main            ,1740.3
921.7416
River Rch & RM=DICKSCK,Main            ,535
971.1068
Boundary for River Rch & Prof#=DICKSCK,Main            , 1
Up Type= 0
Dn Type= 3
Dn Slope=0.034
DSS Import GetInterval= 0
DSS Import GetPeak= 0
DSS Import FillOption= 0

--- DICKSCK.g01 (geometry) ---

Geom Title=USGS 10m DEM
Program Version=4.10

River Reach=DICKSCK         ,Main
Reach XY= 30
     1730486.995      440173.527     1730478.141      440190.715
     1730463.166      440204.941     1730452.101      440212.438
     1730255.224      440286.027     1730183.349      440324.048
     1730118.766      440370.402      1730108.87      440383.944
      1730076.68      440413.638     1729994.049      440460.064
     1729790.186      440607.223     1729737.105      440650.291
     1729681.197       440687.76     1729634.926      440724.005
      1729615.35      440736.831     1729596.449      440743.582
     1729573.497      440748.307     1729512.068      440783.409
     1729478.316      440812.436      1729454.69      440838.088
     1729433.088       440869.14     1729416.887      440898.841
     1729389.211      440984.572     1729358.188       441060.86
     1729344.876      441091.675     1729301.455      441168.183
     1729285.929      441201.261     1729271.078      441239.738
     1729260.337      441276.379       1729180.2      441597.343

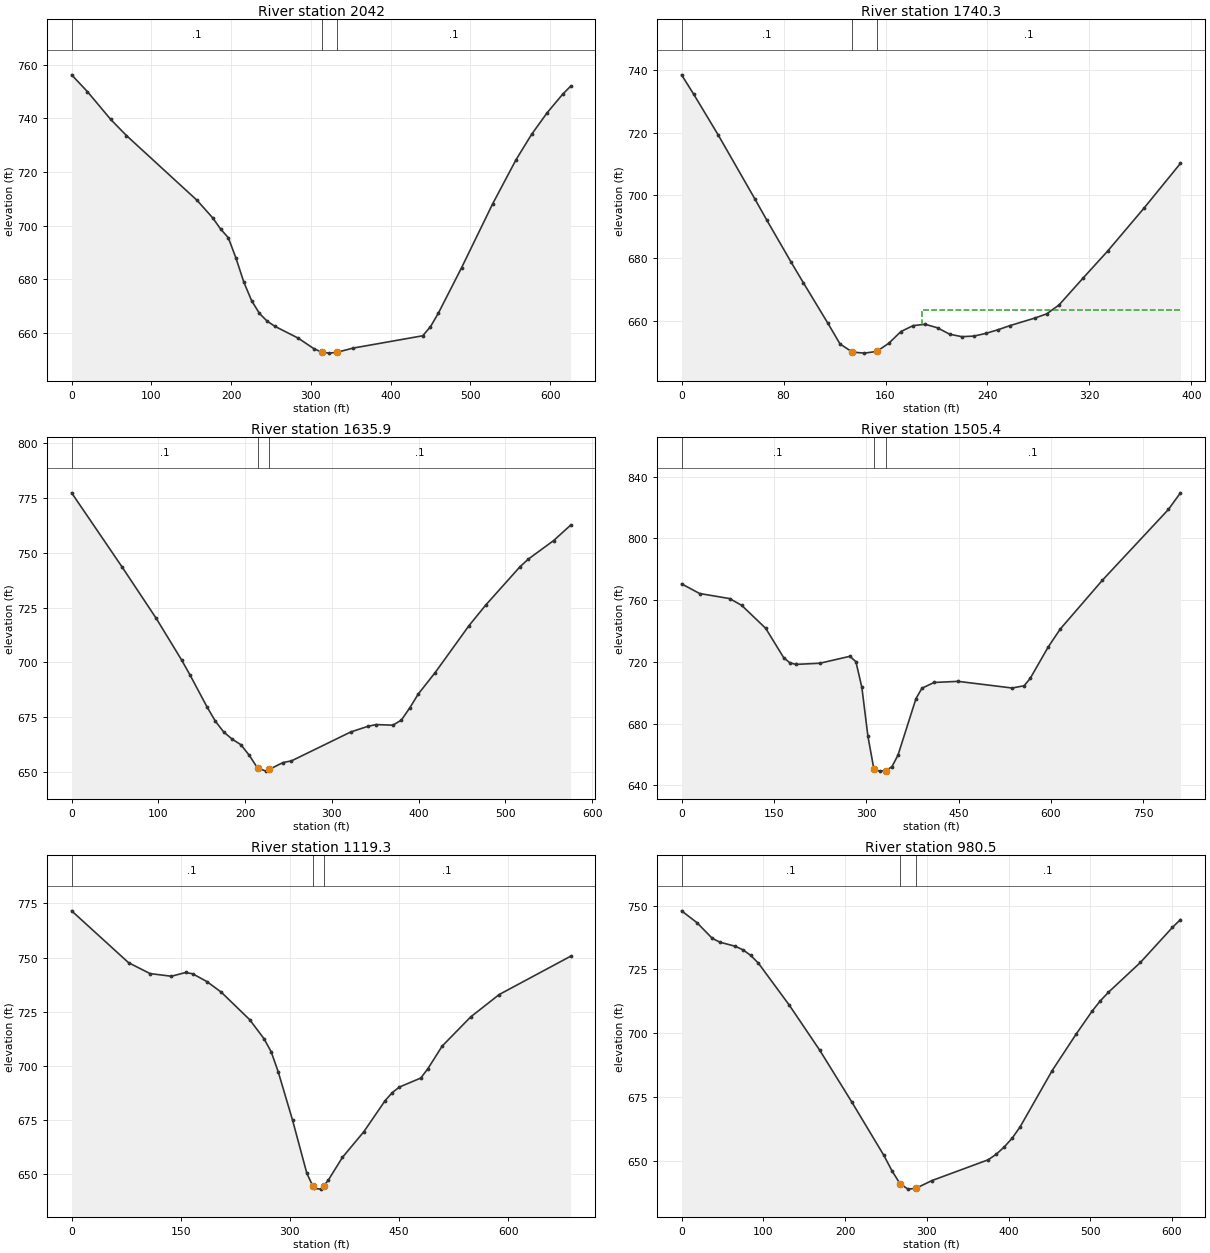
Type RM Length L Ch R = 1 ,2042    ,300,301.6,303.2
XS GIS Cut Line= 3
     1730218.234      440068.419     1730404.769      440077.242
     1730656.842      440436.447
#Sta/Elev= 30
       0  756.25    19.7  750.03    49.1  739.61    68.8  733.62   157.3  709.49
   176.9  702.97   186.7  698.84   196.5  695.55   206.2  687.88     216  678.96
   225.8  672.07   235.5  667.36   245.2  664.48     255  662.54   284.3  658.12
   303.8  654.21   313.5  652.95   323.3  652.56     333  652.89   352.5  654.41
   440.3  659.03     450  662.41   459.8  667.41     489  684.39     528  708.21
   557.3  724.63   576.8  734.07   596.3  742.12   615.8  749.04   625.6  751.97
#Mann= 3 , 0 , 0
       0      .1       0   313.5    .045       0     333      .1       0
Bank Sta=313.5,333
XS Rating Curve= 0 ,0
Exp/Cntr=0.3,0.1

Type RM Length L Ch R = 1 ,1740.3  ,104.9,104.4,104
XS GIS Cut Line= 3
     1730139.411       440185.43     1730233.161      440352.097
      1730372.05      440496.194
#Sta/Elev= 30
       0  738.58     9.6  732.33    28.7  719.39    57.4  698.98    66.9  692.11
      86  678.65    95.6  672.07   114.7  659.22   124.3  652.55   133.9  649.94
   143.4   649.6     153  650.13   162.5  652.72   172.1  656.51   181.7   658.4
   191.2  658.82   200.8  657.69   210.3  655.66   219.8  654.86   229.4  655.05
   238.9  655.93   248.4   657.1   257.9  658.43     277  660.79   286.5  662.16
   296.1  664.99   315.1  673.64   334.2   682.2   362.8  695.96   391.4  710.28
#Mann= 3 , 0 , 0
       0      .1       0   133.9    .045       0     153      .1       0
#XS Ineff= 2 , 0
                          188.95           663.5
Permanent Ineff=
       F       F
Bank Sta=133.9,153
XS Rating Curve= 0 ,0
Exp/Cntr=0.3,0.1

Type RM Length L Ch R = 1 ,1635.9  ,122.4,130.5,137.2
XS GIS Cut Line= 2
      1730010.34      440177.515      1730302.77      440672.717
#Sta/Elev= 30
       0  777.15    58.5  743.24    97.5  720.08   126.7   701.2   136.5  694.31
     156  679.86   165.7   673.3   175.4  668.36   185.2   665.1     195  662.64
   204.7  657.83   214.4  651.97   224.2  650.59   228.1  651.42   243.7   654.5
   253.4  655.24   321.7  668.39   341.2  670.92   350.9  671.76   370.4  671.49
   380.2  673.83   389.9  679.42   399.6  685.67   419.1  695.42   458.1  716.77
   477.6  726.22   516.6  743.42   526.4     747   555.6  755.43   575.1  762.41
#Mann= 3 , 0 , 0
       0      .1       0   214.4    .045       0   228.1      .1       0
Bank Sta=214.4,228.1
XS Rating Curve= 0 ,0
Exp/Cntr=0.3,0.1

Type RM Length L Ch R = 1 ,1505.4  ,386.6,386.1,386.3
XS GIS Cut Line= 2
     1729953.421      440139.639     1730126.363      440931.133
#Sta/Elev= 30
       0  770.56    29.3   764.3    78.1  761.01    97.6  756.64   136.6  741.76
   165.9  722.69   175.7  719.44   185.5  718.36   224.5  719.11   273.3   723.6
   283.1  720.15   292.8  703.45   302.6  671.86   312.4  650.37   322.1   649.2
   331.9  649.57   341.6  652.06   351.4  659.48   380.7  696.22   390.4  702.93
     410  706.65     449  707.37   536.9  703.06   556.4  704.53   566.1  709.25
   595.4  729.64     615  741.29   683.3  772.86   790.6  818.75   810.2  829.54
#Mann= 3 , 0 , 0
       0      .1       0   312.4    .045       0   331.9      .1       0
Bank Sta=312.4,331.9
XS Rating Curve= 0 ,0
Exp/Cntr=0.3,0.1

Type RM Length L Ch R = 1 ,1119.3  ,146.7,138.8,131.4
XS GIS Cut Line= 2
     1729630.902      440340.659     1729784.667      441008.655
#Sta/Elev= 30
       0  771.58    78.3  747.63   107.7  742.62   137.1  741.39   156.7  743.12
   166.5   742.5     186  738.91   205.6  734.04   244.8   721.3   264.4  712.53
   274.2  706.54     284  697.15   303.6  674.93   323.2  650.44   331.3  644.63
   332.9  643.48   342.7  643.14   346.3  644.63   352.5  647.19   372.1  657.79
   401.5  669.63   430.9  684.04   440.7  687.72   450.4  690.25   479.8  694.42
   489.6  698.76   509.2  709.18   548.4  722.64   587.5  732.95   685.5   750.6
#Mann= 3 , 0 , 0
       0      .1       0   331.3    .045       0   346.3      .1       0
Bank Sta=331.3,346.3
XS Rating Curve= 0 ,0
Exp/Cntr=0.3,0.1

Type RM Length L Ch R = 1 ,980.5   ,320.6,307.3,292.6
XS GIS Cut Line= 3
     1729413.992      440527.242     1729532.077      440648.219
     1729761.214      441025.289
#Sta/Elev= 30
       0  747.96    18.8  743.33    37.6  737.16      47  735.66    65.7  734.06
    75.1  732.67    84.5  730.51    93.9  727.47   131.5   711.1     169   693.3
   208.3  672.95   247.5  652.03   257.3  646.05   267.1  640.99   276.9  638.81
   286.7  639.14   306.3  642.17     375  650.31   384.8  652.45   394.6  655.31
   404.4  658.78   414.2  663.26   453.4  685.33   482.8  699.67   502.4   708.7
   512.2  712.63     522  715.96   561.3  727.72   600.5  741.47   610.3  744.54
#Mann= 3 , 0 , 0
       0      .1       0   267.1    .045       0   286.7      .1       0
Bank Sta=267.1,286.7
XS Rating Curve= 0 ,0
Exp/Cntr=0.3,0.1

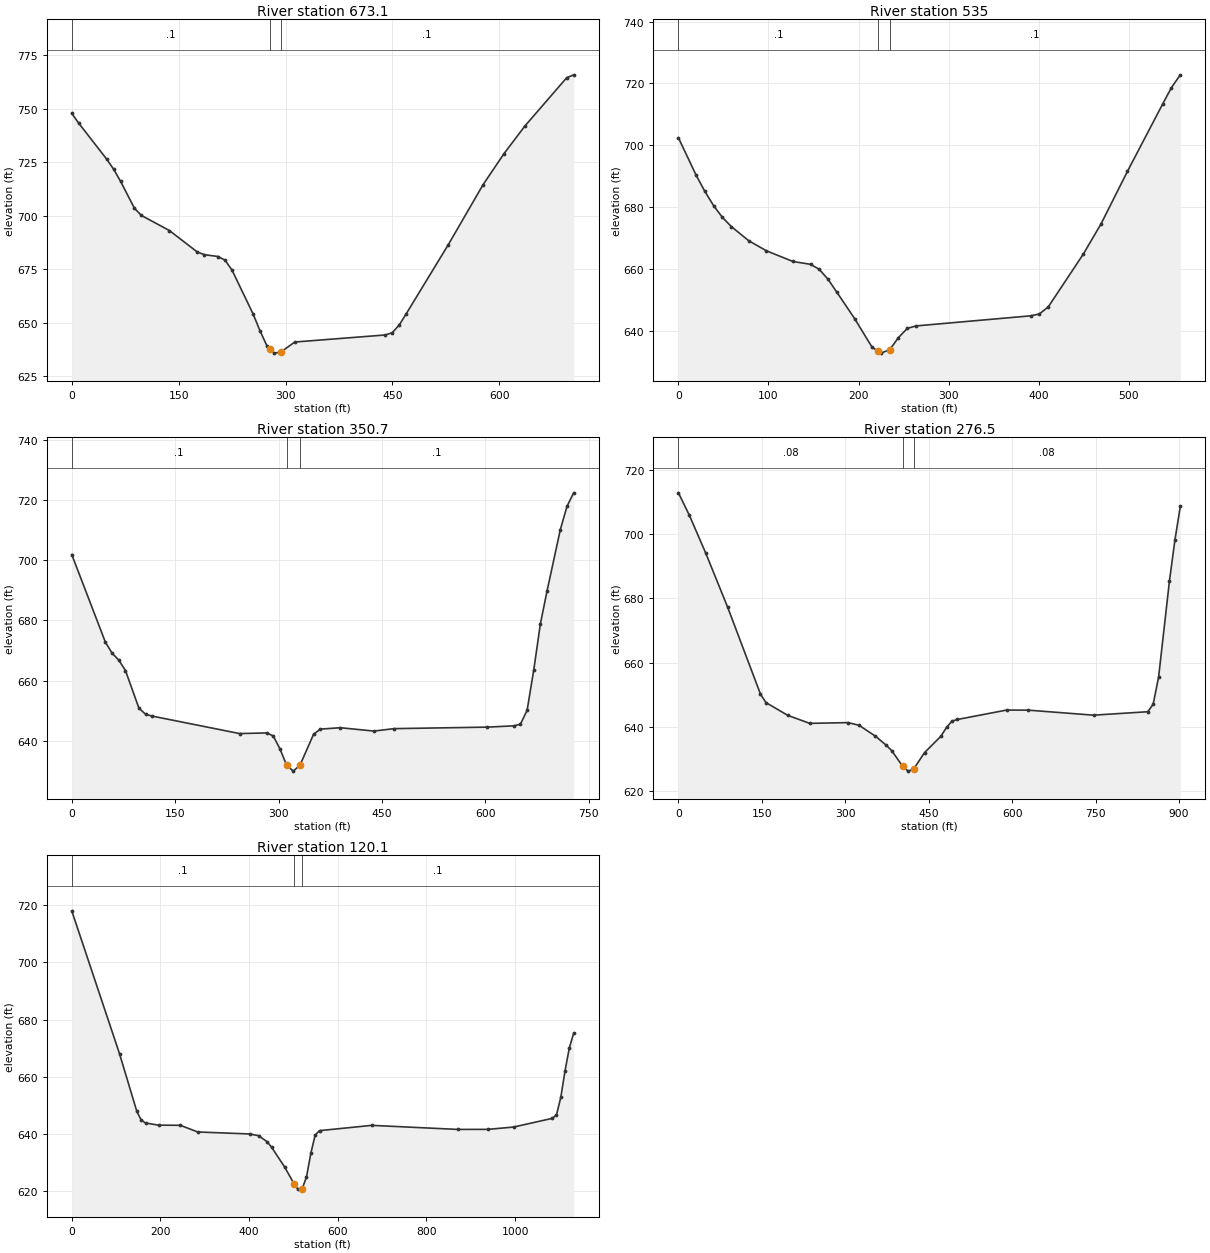
Type RM Length L Ch R = 1 ,673.1   ,139.1,138.1,137.1
XS GIS Cut Line= 2
      1729132.88      440852.467      1729781.97      441125.967
#Sta/Elev= 30
       0  747.73     9.8  743.15    48.9   726.4    58.7  721.68    68.5  715.98
      88  703.38    97.8  700.03     137  692.99   176.1  682.99   185.9  681.72
   205.4  680.85   215.2  679.11     225  674.44   254.4  654.08   264.1  646.21
   273.9  639.13   278.4  637.56   283.7   635.7   293.4  636.19     313  640.89
   440.2  644.19     450  645.28   459.8  648.96   469.6  654.19   528.3  686.28
   577.2  714.38   606.5  728.85   635.9   741.8   694.6  764.39   704.4  765.75
#Mann= 3 , 0 , 0
       0      .1       0   278.4    .045       0   293.4      .1       0
Bank Sta=278.4,293.4
XS Rating Curve= 0 ,0
Exp/Cntr=0.3,0.1

Type RM Length L Ch R = 1 ,535     ,184.5,184.3,183.8
XS GIS Cut Line= 2
     1729129.777      441012.124     1729652.669      441205.073
#Sta/Elev= 30
       0  702.43    19.6  690.37    29.3  685.12    39.1  680.47    48.9  676.67
    58.7  673.74    78.2  669.12    97.8  665.88   127.1  662.44   146.7  661.52
   156.4   659.9   166.2  656.66     176  652.48   195.6     644   215.1  634.71
   221.8  633.41   224.9  632.81   234.7  633.93   244.4  637.85   254.2  640.82
     264  641.61   391.1  644.87   400.9  645.48   410.7  647.74   449.8  664.89
   469.4  674.62   498.7  691.59   537.8  713.35   547.6  718.68   557.4  722.78
#Mann= 3 , 0 , 0
       0      .1       0   221.8    .045       0   234.7      .1       0
Bank Sta=221.8,234.7
XS Rating Curve= 0 ,0
Exp/Cntr=0.3,0.1

Type RM Length L Ch R = 1 ,350.7   ,74.2,74.3,74.3
XS GIS Cut Line= 3
      1728961.99      441150.479     1729403.039      441305.632
     1729653.312      441233.372
#Sta/Elev= 30
       0  701.87    48.7  672.84    58.4  669.18    68.2  666.85    77.9  663.39
    97.4  650.91   107.2  648.86   116.9  648.26   243.5  642.47   282.5  642.68
   292.2  641.72     302  637.38   311.7  631.96   321.4  630.01   331.2  632.06
   350.7  642.21   360.4  643.95   389.6  644.41   438.3   643.3   467.5  644.11
   602.6  644.61   641.2  645.03   650.8   645.6   660.5  650.19   670.2   663.7
   679.8  678.94   689.4  689.78   708.7  710.16   718.4  717.91     728  722.35
#Mann= 3 , 0 , 0
       0      .1       0   311.7    .045       0   331.2      .1       0
Bank Sta=311.7,331.2
XS Rating Curve= 0 ,0
Exp/Cntr=0.3,0.1

Type RM Length L Ch R = 1 ,276.5   ,156.4,156.4,156.6
XS GIS Cut Line= 3
     1728856.739      441190.627      1729422.05      441391.329
     1729718.914      441334.349
#Sta/Elev= 30
       0  712.89    19.7  705.88    49.2  694.07    88.5  677.26   147.5   650.2
   157.4  647.55   196.7  643.57     236  641.09   304.9  641.32   324.5  640.51
     354  637.11   373.7  634.26   383.5  632.57   403.2  627.69     413  626.21
   422.9   626.9   442.5  631.99     472  637.11   481.9  639.82   491.7  641.78
   501.5   642.3     590  645.23   629.1   645.2   746.2  643.64   843.7  644.71
   853.4  647.06   863.2  655.55   882.7  685.49   892.4  698.08   902.2  708.69
#Mann= 3 , 0 , 0
       0     .08       0   403.2    .045       0   422.9     .08       0
Bank Sta=403.2,422.9
XS Rating Curve= 0 ,0
Exp/Cntr=0.3,0.1

Type RM Length L Ch R = 1 ,120.1   ,122.2,120.1,117.6
XS GIS Cut Line= 4
     1728806.826      441197.137     1728978.634      441398.022
     1729412.769      441554.311     1729810.515       441471.66
#Sta/Elev= 30
       0     718   107.7  668.08   146.8   647.9   156.6  644.91   166.4  643.88
   195.8  643.12   244.8  643.07     284  640.74   401.8  640.04   421.4  639.44
     441  637.28   450.9  635.37   480.3  628.45   501.3  622.65   509.8  620.77
   519.6   620.9   529.4  624.97   539.2  633.27     549  639.66   558.8   641.2
   676.7  643.05   870.8  641.63   938.5  641.65   996.6  642.46  1083.6  645.49
  1093.3  646.72    1103  652.82  1112.6  662.14  1122.3  670.15    1132  675.22
#Mann= 3 , 0 , 0
       0      .1       0   501.3    .045       0   519.6      .1       0
Bank Sta=501.3,519.6
XS Rating Curve= 0 ,0
Exp/Cntr=0.3,0.1

Chan Stop Cuts=-1
Use User Specified Reach Order=0
Composite Channel Slope=5